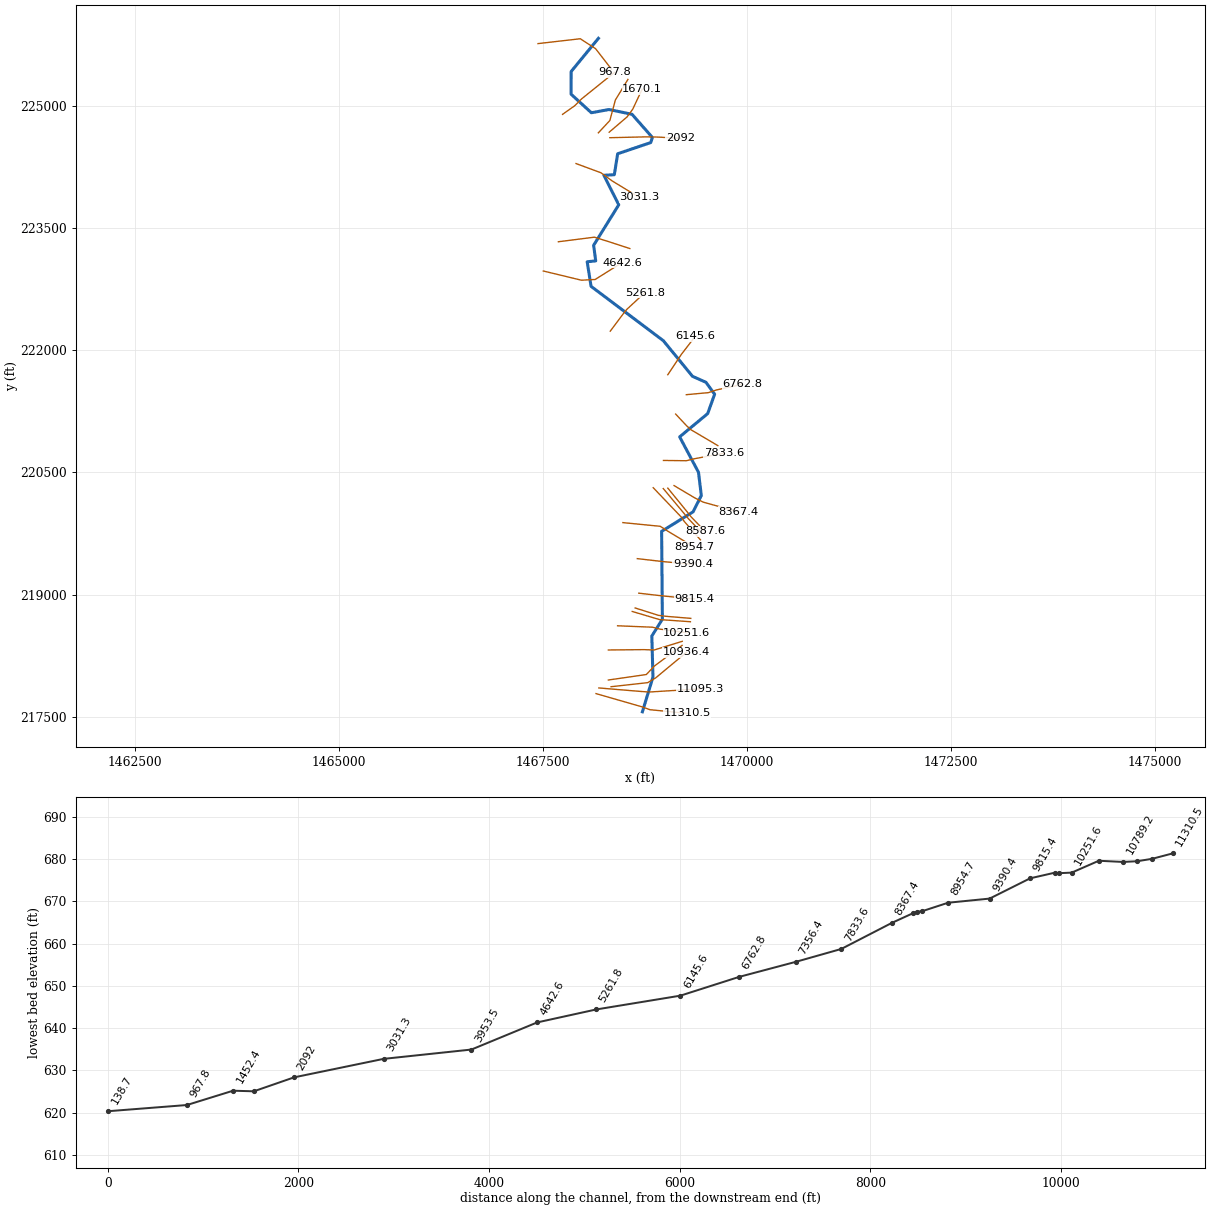
--- BGSLNDRN.prj (project) ---

Proj Title=BGSLNDRN
Current Plan=p01
Default Exp/Contr=0,0
English Units
Geom File=g01
Flow File=f01
Plan File=p01
BEGIN DESCRIPTION:
END DESCRIPTION:
DSS Export Rating Curves= 0
DSS Export Rating Curve Sorted= 0
DSS Export Volume Flow Curves= 0
DXF OffsetX= 0
DXF OffsetY= 0
DXF ScaleX= 0
DXF ScaleY= 0

--- BGSLNDRN.p01 (plan) ---

Plan Title=Floodplain
Program Version=4.00
Geom File=g01
Flow File=f01
K Sum by GR=0
Std Step Tol=0.01
Critical Tol=0.01
Num of Std Step Trials=20
Max Error Tol=0.3
Flow Tol Ratio=0.001
Split Flow NTrial=30
Split Flow Tol=0.02
Split Flow Ratio=0.02
Log Output Level=0
Friction Slope Method=1
Unsteady Friction Slope Method=2
Unsteady Bridges Friction Slope Method=1
Global Log Level=0
CheckData=False
Run HTab=0
Run UNet=0
Run PostProcess=0
UNET Theta=0
UNET Theta Warmup=0
UNET ZTol=0
UNET ZSATol=0
UNET MxIter=0
UNET MaxInSteps=0
UNET DtIC=0
UNET DtMin=0
UNET MaxCRTS=0
UNET WFStab=0
UNET SFStab=0
UNET WFX=0
UNET SFX=0
UNET DSS MLevel=0
UNET DZMax Abort=0
UNET Convert EG Bridges=0
UNET Use Existing IB Tables=0
UNET Froude Limit=0
UNET Froude Power=0
Write IC File=0
Echo Input=False
Echo Output=False
Write Detailed=0

--- BGSLNDRN.f01 (steady flow) ---

Flow Title=NFF Regression Equation
Program Version=4.10
Number of Profiles= 1
Profile Names=P100yr
River Rch & RM=BGSLNDRN,Main            ,11310.5
  1301.2
River Rch & RM=BGSLNDRN,Main            ,8954.7
1342.431
River Rch & RM=BGSLNDRN,Main            ,8685.9
1492.714
River Rch & RM=BGSLNDRN,Main            ,5261.8
1550.659
River Rch & RM=BGSLNDRN,Main            ,138.7
1661.377
Boundary for River Rch & Prof#=BGSLNDRN,Main            , 1
Up Type= 0
Dn Type= 3
Dn Slope=0.0014
DSS Import GetInterval= 0
DSS Import GetPeak= 0
DSS Import FillOption= 0

--- BGSLNDRN.g01 (geometry) ---

Geom Title=USGS 10m DEM
Program Version=4.10

River Reach=BGSLNDRN        ,Main
Reach XY= 30
     1468718.144      217558.822     1468847.311      217985.906
     1468833.422      218489.378     1468962.694      218696.781
     1468953.579      219776.208     1469339.404      220016.428
     1469439.735      220216.177     1469405.302        220501.8
       1469174.5      220937.232     1469517.815      221223.256
     1469602.885      221461.538     1469496.116      221608.145
     1469332.052      221681.156     1468974.847      222118.656
     1468088.996      222787.492     1468041.687      223089.142
     1468146.288      223099.992     1468120.246      223291.399
     1468428.406      223788.795     1468246.114      224151.642
     1468374.152       224159.02     1468414.951      224416.399
     1468819.546      224553.552     1468840.813      224616.051
     1468591.247      224901.208      1468309.13      224960.235
     1468092.984      224920.305      1467844.72       225148.17
     1467845.084      225426.836     1468179.235      225834.811

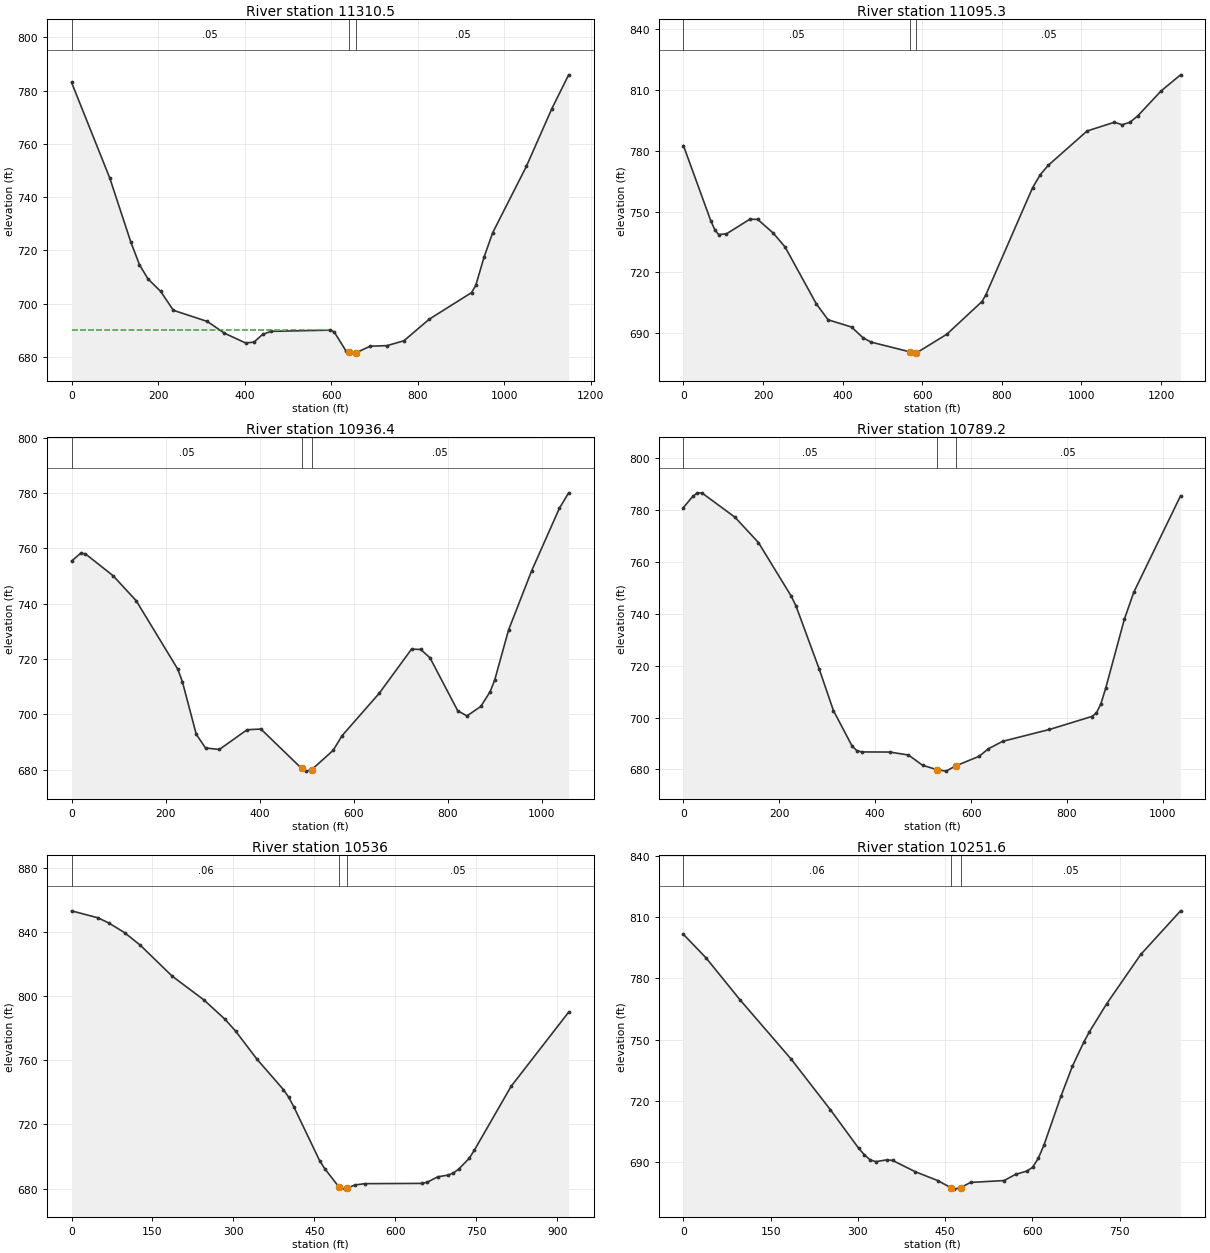
Type RM Length L Ch R = 1 ,11310.5 ,208.6,215.3,222.1
XS GIS Cut Line= 4
     1468149.458      217782.378     1468714.996      217619.184
     1468810.482      217584.461     1469267.079      217539.323
#Sta/Elev= 30
       0  783.08    88.3  747.17   137.3  722.98     157   714.6   176.6  709.27
     206  704.55   235.4  697.45   313.9  693.26   353.2  688.87   402.2  685.19
   421.8   685.5   441.5  688.37   461.1  689.54   597.8  689.99   607.1  689.33
   634.8  682.08  640.94681.6107   652.5  681.36  657.74681.4999   690.2  683.96
   729.3  684.18   768.3  686.01   826.9  694.12   924.5  704.09   934.3  706.81
   953.8  717.58   973.3  726.55  1051.4  751.55    1110  773.13    1149   785.9
#Mann= 3 , 0 , 0
       0     .05       0  640.94    .045       0  657.74     .05       0
#XS Ineff= 2 , 0
          597.93  690.11
Permanent Ineff=
       F       F
Bank Sta=640.94,657.74
XS Rating Curve= 0 ,0
Exp/Cntr=0.3,0.1

Type RM Length L Ch R = 1 ,11095.3 ,142.5,158.8,185.1
XS GIS Cut Line= 4
      1468184.18      217851.823     1468702.843       217808.42
      1468804.84      217801.909      1469429.84      217840.972
#Sta/Elev= 30
       0  782.57    68.7  745.45    78.6  741.11    88.4  738.64     108  738.98
     167  746.21   186.6  746.12   225.9  739.29   255.3  732.52   333.9  704.39
   363.4  696.55   422.3  692.96   451.7  687.58   471.4  685.53   570.3  680.64
   576.2  680.08   585.3  680.17   661.8  689.43   749.9  705.53   759.7  708.84
   877.1  761.74   896.6  768.23   916.2  772.77  1014.1  789.77  1082.6  794.08
  1102.1  792.85  1121.7  794.06  1141.3  797.22    1200  809.55  1248.9   817.5
#Mann= 3 , 0 , 0
       0     .05       0   570.3    .045       0   585.3     .05       0
Bank Sta=570.3,585.3
XS Rating Curve= 0 ,0
Exp/Cntr=0.3,0.1

Type RM Length L Ch R = 1 ,10936.4 ,140.8,147.3,144.7
XS GIS Cut Line= 4
     1468333.919      217867.014     1468783.138      217916.927
     1468880.794       217975.52     1469258.399      218290.191
#Sta/Elev= 30
       0  755.41    19.6  758.27    29.5  758.03    88.4  750.13   137.6  741.08
     226  716.35   235.8  711.83   265.3  692.82     285  687.88   314.4  687.32
   373.4  694.46   402.8  694.71   489.5  680.47   499.4   679.5   510.7680.0209
   556.4  686.98   575.7  692.36   654.3  707.59   723.2  723.59   742.8  723.48
   762.5  720.45   821.5  701.32   841.1  699.46   870.6  702.89   890.3  708.19
   900.1  712.42   929.6  730.51   978.8  751.94  1037.7   774.5  1057.4  780.08
#Mann= 3 , 0 , 0
       0     .05       0   489.5    .045       0   510.7     .05       0
Bank Sta=489.5,510.7
XS Rating Curve= 0 ,0
Exp/Cntr=0.3,0.1

Type RM Length L Ch R = 1 ,10789.2 ,274,253.1,227.4
XS GIS Cut Line= 4
     1468301.367      217949.479     1468765.777      218016.753
     1468867.774       218123.09     1469204.145      218374.826
#Sta/Elev= 30
       0  781.07    19.6   785.4    29.3  786.74    39.1  786.63   107.5  777.32
   156.4  767.55   224.8  746.86   234.6  743.14   283.5  718.56   312.8  702.71
   351.9  688.95   361.7  687.25   371.5  686.75   430.2   686.7   469.3  685.56
   498.7  681.61   528.2  679.93   547.8  679.34   567.5  681.34   616.6  685.06
   636.1  687.98   665.5  690.83   763.2  695.41   851.1   700.4   860.9  701.66
   870.6  705.35   880.4  711.24   919.5  737.96     939  748.32  1036.7  785.59
#Mann= 3 , 0 , 0
       0     .05       0   528.2    .045       0   567.5     .05       0
Bank Sta=528.2,567.5
XS Rating Curve= 0 ,0
Exp/Cntr=0.3,0.1

Type RM Length L Ch R = 1 ,10536   ,287.8,284.4,279.7
XS GIS Cut Line= 4
     1468301.367      218318.402     1468733.225      218322.743
     1468863.433      218318.402     1469206.315      218424.739
#Sta/Elev= 30
       0  853.34    49.1  848.97    68.7  845.82    98.2  839.74   127.6  831.84
   186.5  812.58   245.4  797.71   284.6   785.6   304.3  778.17   343.5  760.79
   392.6  741.78   402.4  737.03   412.2  730.84   459.8  697.35   469.1  692.46
  496.19 680.687   506.3  679.62  509.87680.1161   524.9   682.2   543.6  683.03
   649.5   683.2   659.2  683.94   678.6  687.31     698  688.38   707.7  689.73
   717.4   692.1   736.8   698.8   746.5  703.93   814.4   743.7   921.2  790.09
#Mann= 3 , 0 , 0
       0     .06       0  496.19    .045       0  509.87     .05       0
Bank Sta=496.19,509.87
XS Rating Curve= 0 ,0
Exp/Cntr=0.3,0.1

Type RM Length L Ch R = 1 ,10251.6 ,124.9,130.2,133.6
XS GIS Cut Line= 4
     1468414.215      218615.711     1468841.732       218598.35
     1468932.878      218574.479     1469262.739      218531.076
#Sta/Elev= 30
       0  801.62    38.9  790.09    97.2  769.59   184.8  740.65   252.8  715.66
   301.4   696.8   311.2   693.6   320.9   691.2   330.6  690.27   350.1  691.16
   359.8  690.86   398.7  685.33   437.3     681   459.5  677.57   465.6  676.81
  476.67677.5636   493.8   680.1   551.4  681.01     571  684.04   590.6  685.66
   600.4  687.51   610.2  691.92   619.9  698.38   649.3  722.46   668.9  737.08
   688.4  748.84   698.2  753.95   727.6  767.56   786.3  791.76   854.8  813.15
#Mann= 3 , 0 , 0
       0     .06       0   459.5    .045       0  476.67     .05       0
Bank Sta=459.5,476.67
XS Rating Curve= 0 ,0
Exp/Cntr=0.3,0.1

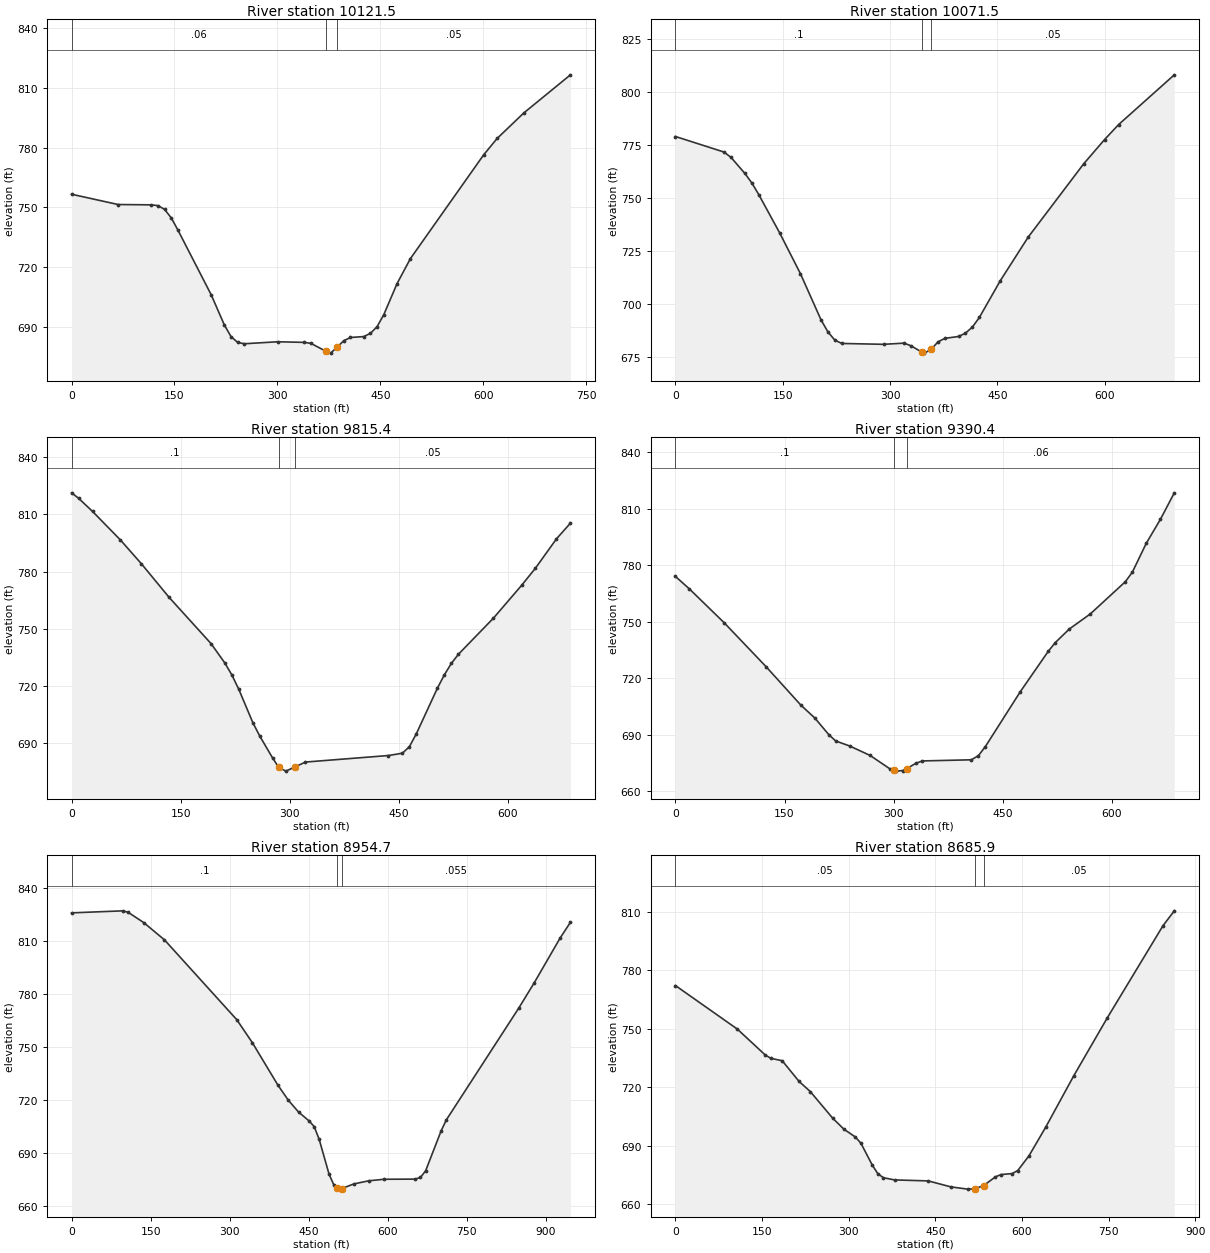
Type RM Length L Ch R = 1 ,10121.5 ,51.9,49.9,47.9
XS GIS Cut Line= 4
     1468594.336      218791.493     1468928.538      218691.666
     1468995.812      218687.326     1469306.142      218665.625
#Sta/Elev= 30
       0  756.53    67.8  751.37   116.3   751.2     126  750.81   135.6  748.92
   145.3  744.64     155  738.53   203.5  706.02   222.8  690.76   232.5  684.96
   242.2  682.05   251.9  681.39   300.4  682.39   339.1  682.08   348.8  681.61
   371.1  677.55   377.7  676.68   387.3  679.76     397  682.97   406.6  684.54
   425.9     685   435.6  686.59   445.4  689.99   455.1  695.95   474.5  711.62
     494   724.2   600.9   776.4   620.4  784.57   659.2  797.36   727.3  816.55
#Mann= 3 , 0 , 0
       0     .06       0   371.1    .045       0   387.3     .05       0
Bank Sta=371.1,387.3
XS Rating Curve= 0 ,0
Exp/Cntr=0.3,0.1

Type RM Length L Ch R = 1 ,10071.5 ,255,256.1,256.2
XS GIS Cut Line= 4
     1468629.058      218834.895     1468915.517       218743.75
     1469000.152      218732.899     1469310.482      218706.857
#Sta/Elev= 30
       0   779.1    67.9  771.75    77.6  769.24      97  761.68   106.7  757.19
   116.4  751.69   145.5  733.68   174.6  714.38   203.6  692.41   213.3  686.73
     223  682.84   232.7  681.35   290.9  680.94   319.6   681.5     329  680.28
     344  677.37     348  676.78   357.5   678.6     367  682.08   376.5  683.75
   395.7  684.64   405.4  686.21   415.1  689.09   424.9  693.66   454.1  710.98
     493  731.52   570.8  766.24     600  777.68   619.5  784.72   697.4  808.23
#Mann= 3 , 0 , 0
       0      .1       0     344    .045       0   357.5     .05       0
Bank Sta=344,357.5
XS Rating Curve= 0 ,0
Exp/Cntr=0.3,0.1

Type RM Length L Ch R = 1 ,9815.4  ,424.8,425,424.8
XS GIS Cut Line= 4
     1468673.619      219016.464     1468930.708      218986.805
     1469011.003      218978.125     1469356.055      218945.573
#Sta/Elev= 30
       0  821.27     9.6  818.42    28.8  811.52    67.1  796.59    95.8  784.19
   134.2  766.46   191.7  742.31   210.9  732.05   220.4  725.85     230  718.29
   249.2  700.91   258.8  693.82   276.7  682.19  284.78677.5036   294.7  675.46
  306.72 677.558   321.6  680.21   435.8  683.64   455.1  684.86   464.7  688.34
   474.3  695.16   503.2  718.99   512.8  725.99   522.5  732.01   532.1  736.72
   580.2  755.61   618.8  772.74     638  781.81   666.9  797.17   686.1  805.38
#Mann= 3 , 0 , 0
       0      .1       0  284.78    .045       0  306.72     .05       0
Bank Sta=284.78,306.72
XS Rating Curve= 0 ,0
Exp/Cntr=0.3,0.1

Type RM Length L Ch R = 1 ,9390.4  ,445.6,435.7,423.4
XS GIS Cut Line= 4
     1468655.389      219440.943     1468912.479      219411.284
     1468992.774      219402.604     1469337.826      219370.052
#Sta/Elev= 30
       0  773.94    19.2  767.33    67.1  749.35   124.6  726.09   172.5  705.67
   191.7  698.82   210.9  690.01   220.4  686.66   239.6     684   267.8  678.96
   294.7  671.93   300.5  671.11   303.7  670.66   312.6  670.96  318.24672.0355
   330.6   674.8   339.6  676.07     407  676.67   416.6  678.85   426.2  683.67
   474.3  712.82   512.8  734.28   522.5   738.9   541.7  746.07   570.6  754.08
   618.8  771.19   628.4  776.24   647.6   791.6   666.9  804.21   686.1  818.33
#Mann= 3 , 0 , 0
       0      .1       0   300.5    .045       0  318.24     .06       0
Bank Sta=300.5,318.24
XS Rating Curve= 0 ,0
Exp/Cntr=0.3,0.1

Type RM Length L Ch R = 1 ,8954.7  ,277.6,268.8,259.2
XS GIS Cut Line= 4
     1468479.174      219883.651     1468937.073      219838.078
     1469023.879      219781.655      1469351.57      219584.172
#Sta/Elev= 30
       0  826.09    97.9  827.24   107.7  826.33   137.1  820.52   176.2  810.79
   313.3  765.62   342.7  752.67   391.6  728.44   411.2  719.99   430.8  713.23
   450.4  708.33   460.2  705.08   469.6   697.9   488.4  678.15   497.8   671.8
  504.17670.3633   507.2  669.68   512.1  669.97   535.5  672.63   563.7  674.39
   593.1  675.27     652  675.35   661.8  676.31   671.6  680.08     701  702.67
   710.8  708.86   848.2  772.15   877.6  786.49   926.7  811.82   946.3  820.75
#Mann= 3 , 0 , 0
       0      .1       0  504.17    .045       0   512.1    .055       0
Bank Sta=504.17,512.1
XS Rating Curve= 0 ,0
Exp/Cntr=0.3,0.1

Type RM Length L Ch R = 1 ,8685.9  ,54.1,56.5,59
XS GIS Cut Line= 4
     1468850.702      220312.471      1469199.66      219946.151
      1469230.91       219897.54     1469428.827      219671.846
#Sta/Elev= 30
       0  772.22     107   749.9   155.7  736.51   165.4  734.85   184.9  733.62
     214  723.02   233.5   717.8   272.4  704.08   291.9  698.43   311.3  694.52
   321.1  691.31   340.5  680.22   350.3  675.67     360  673.56   379.4  672.43
   437.8  671.92   476.7  668.87   505.9   667.7   518.8  667.88   533.8  669.56
   554.1     674   563.7  675.18   583.1  675.69   592.8  677.26   612.1  684.75
   641.2  699.52   689.6  725.81   747.7  755.58   844.5  803.06   863.9   810.6
#Mann= 3 , 0 , 0
       0     .05       0   518.8    .045       0   533.8     .05       0
Bank Sta=518.8,533.8
XS Rating Curve= 0 ,0
Exp/Cntr=0.3,0.1

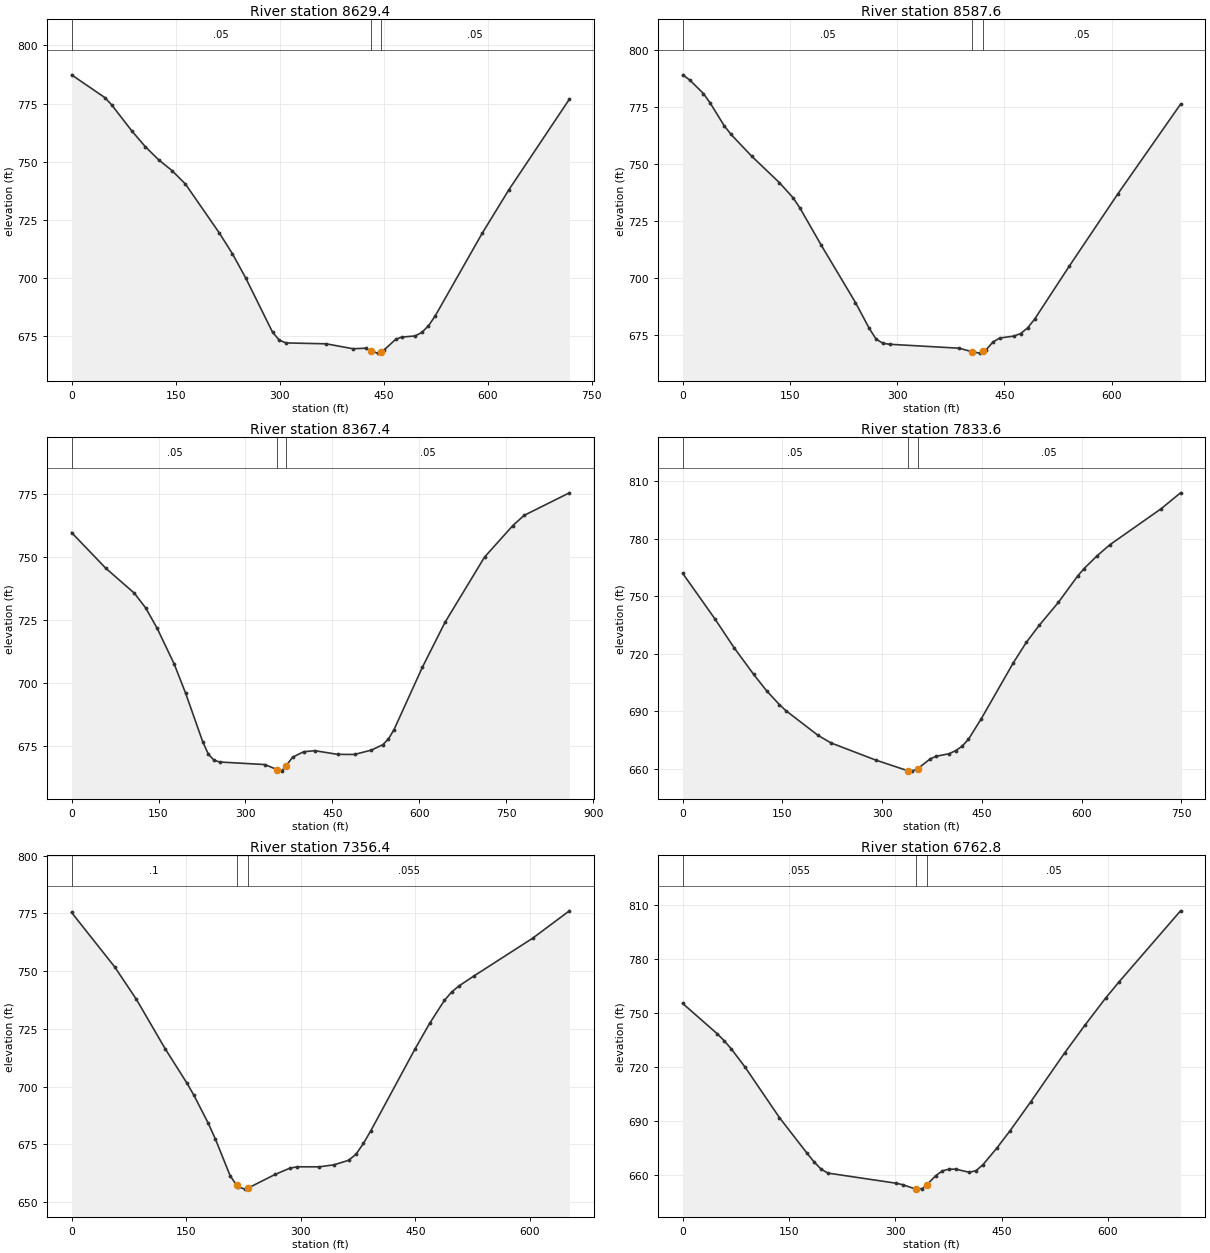
Type RM Length L Ch R = 1 ,8629.4  ,42.3,41.8,41.2
XS GIS Cut Line= 4
     1468973.966      220302.054     1469239.591       219982.61
     1469277.785      219935.735     1469444.452      219760.387
#Sta/Elev= 30
       0  787.35    48.3  777.49      58  774.36      87  763.16   106.3  756.44
   125.6  750.76   144.9  746.12   164.2  740.34   212.6  719.47   231.9  710.36
   251.2  699.85   289.8  676.56   299.5  673.14   309.2  671.94   367.1  671.55
   405.8  669.43   424.1  669.65  431.85668.3793   441.4  667.54  446.15 668.194
     450  668.73   467.3  673.47   475.9  674.45   495.3  674.94     505  676.44
   514.6   679.3   524.3  683.54     592   719.1   630.8  737.98   717.8  776.87
#Mann= 3 , 0 , 0
       0     .05       0  431.85    .045       0  446.15     .05       0
Bank Sta=431.85,446.15
XS Rating Curve= 0 ,0
Exp/Cntr=0.3,0.1

Type RM Length L Ch R = 1 ,8587.6  ,210.1,220.1,230.1
XS GIS Cut Line= 4
     1469029.521      220307.262     1469279.521      219999.971
     1469314.244      219954.832     1469482.646      219779.485
#Sta/Elev= 30
       0  789.32     9.7   787.1      29  781.11    38.6  776.87      58  767.01
    67.6  763.17    96.6  753.59   135.3  741.99   154.6   735.3   164.2  730.76
   193.2  714.86   241.6  689.42   260.9  678.06   270.5  673.35   280.2  671.49
   289.9  671.09   386.5  669.37  404.87667.8114   415.1  667.21  420.53 668.115
   424.6  668.79   434.1  672.16   443.6  673.85   462.8  674.66   472.5  675.79
   482.3  678.26     492  682.05   540.6  705.37   608.7  737.16   696.2  776.42
#Mann= 3 , 0 , 0
       0     .05       0  404.87    .045       0  420.53     .05       0
Bank Sta=404.87,420.53
XS Rating Curve= 0 ,0
Exp/Cntr=0.3,0.1

Type RM Length L Ch R = 1 ,8367.4  ,517.8,533.8,549.6
XS GIS Cut Line= 4
      1469105.91      220338.512     1469359.382      220187.471
     1469461.813      220135.387     1469894.105      220015.596
#Sta/Elev= 30
       0  759.68      59  745.51   108.2  735.62   127.9  729.72   147.5  721.71
     177  707.49   196.7   695.9   226.2  676.64     236  671.65   245.9  669.24
   255.7  668.56   333.4  667.55   354.9  665.52   362.1  664.94   369.9  667.04
   381.2  670.47   400.4  672.64   419.7  673.06   458.7   671.6     488  671.56
   517.2   673.3   536.8  675.43   546.5  677.69   556.2  681.45     605  706.15
     644  723.98   712.3  749.93     761  762.42   780.5  766.48   858.6  775.44
#Mann= 3 , 0 , 0
       0     .05       0   354.9    .045       0   369.9     .05       0
Bank Sta=354.9,369.9
XS Rating Curve= 0 ,0
Exp/Cntr=0.3,0.1

Type RM Length L Ch R = 1 ,7833.6  ,498.7,477.2,453.6
XS GIS Cut Line= 4
     1468975.702       220647.54     1469256.952      220644.068
     1469354.174      220668.374     1469715.285      220736.082
#Sta/Elev= 30
       0  761.99    48.5  738.18    77.6  723.01   106.7  709.26   126.1  700.72
   145.5  693.46   155.2  690.31   203.7  677.37   223.1  673.45   290.4   664.5
   338.4  658.96     345  658.73   353.4  659.96   372.4  665.14   381.5   666.5
   400.8  667.82   410.5  669.41   420.2  671.71   429.8  675.32   449.2   686.1
   497.5  715.36   516.8   725.9   536.2   734.8   565.2  746.85   594.2  760.61
   603.9   764.5   623.2  771.08   642.5  776.88   719.9  795.75   748.9  804.01
#Mann= 3 , 0 , 0
       0     .05       0   338.4    .045       0   353.4     .05       0
Bank Sta=338.4,353.4
XS Rating Curve= 0 ,0
Exp/Cntr=0.3,0.1

Type RM Length L Ch R = 1 ,7356.4  ,568.7,593.7,617.5
XS GIS Cut Line= 4
     1469125.392      221217.348     1469260.424      221072.887
     1469310.771      221026.012     1469642.369      220829.832
#Sta/Elev= 30
       0  775.46    56.5  751.86    84.8  737.88   122.4  716.54   150.7  701.76
   160.1  696.39   178.9  684.24   188.3  677.39   207.6  661.52   216.1  657.37
   217.4  656.73   227.2  655.68   231.1  656.14   266.5  662.04   285.8  664.75
   295.4  665.35   324.3  665.33   343.6  666.21   362.8  668.17   372.5  670.82
   382.1  675.46   391.8  680.94   449.5  716.23   468.8  727.43   488.1  737.34
   497.7  741.03   507.3  743.65   526.6   747.9   603.7  764.29   651.8  776.15
#Mann= 3 , 0 , 0
       0      .1       0   216.1    .045       0   231.1    .055       0
Bank Sta=216.1,231.1
XS Rating Curve= 0 ,0
Exp/Cntr=0.3,0.1

Type RM Length L Ch R = 1 ,6762.8  ,601.1,617.2,630.8
XS GIS Cut Line= 4
     1469255.934      221455.652     1469527.785      221480.874
     1469625.007       221513.86     1469944.452      221583.304
#Sta/Elev= 30
       0  755.25    48.8  738.39    58.5  734.56    68.2  730.18    87.8  720.03
   136.5  691.87   175.5  672.05   185.3  667.32     195  663.32   204.8  661.04
     301  655.42   310.4   654.6     329  652.12   338.4  652.46  344.62654.5579
     357  659.55   366.4  662.27   375.7  663.17   385.3  663.22   404.5  661.47
   414.1  662.42   423.8  665.72     443  674.75   462.2  684.65   491.1  700.57
   539.1  727.82     568  743.34   596.8  758.19   616.1  767.35   702.6  806.69
#Mann= 3 , 0 , 0
       0    .055       0     329    .045       0  344.62     .05       0
Bank Sta=329,344.62
XS Rating Curve= 0 ,0
Exp/Cntr=0.3,0.1

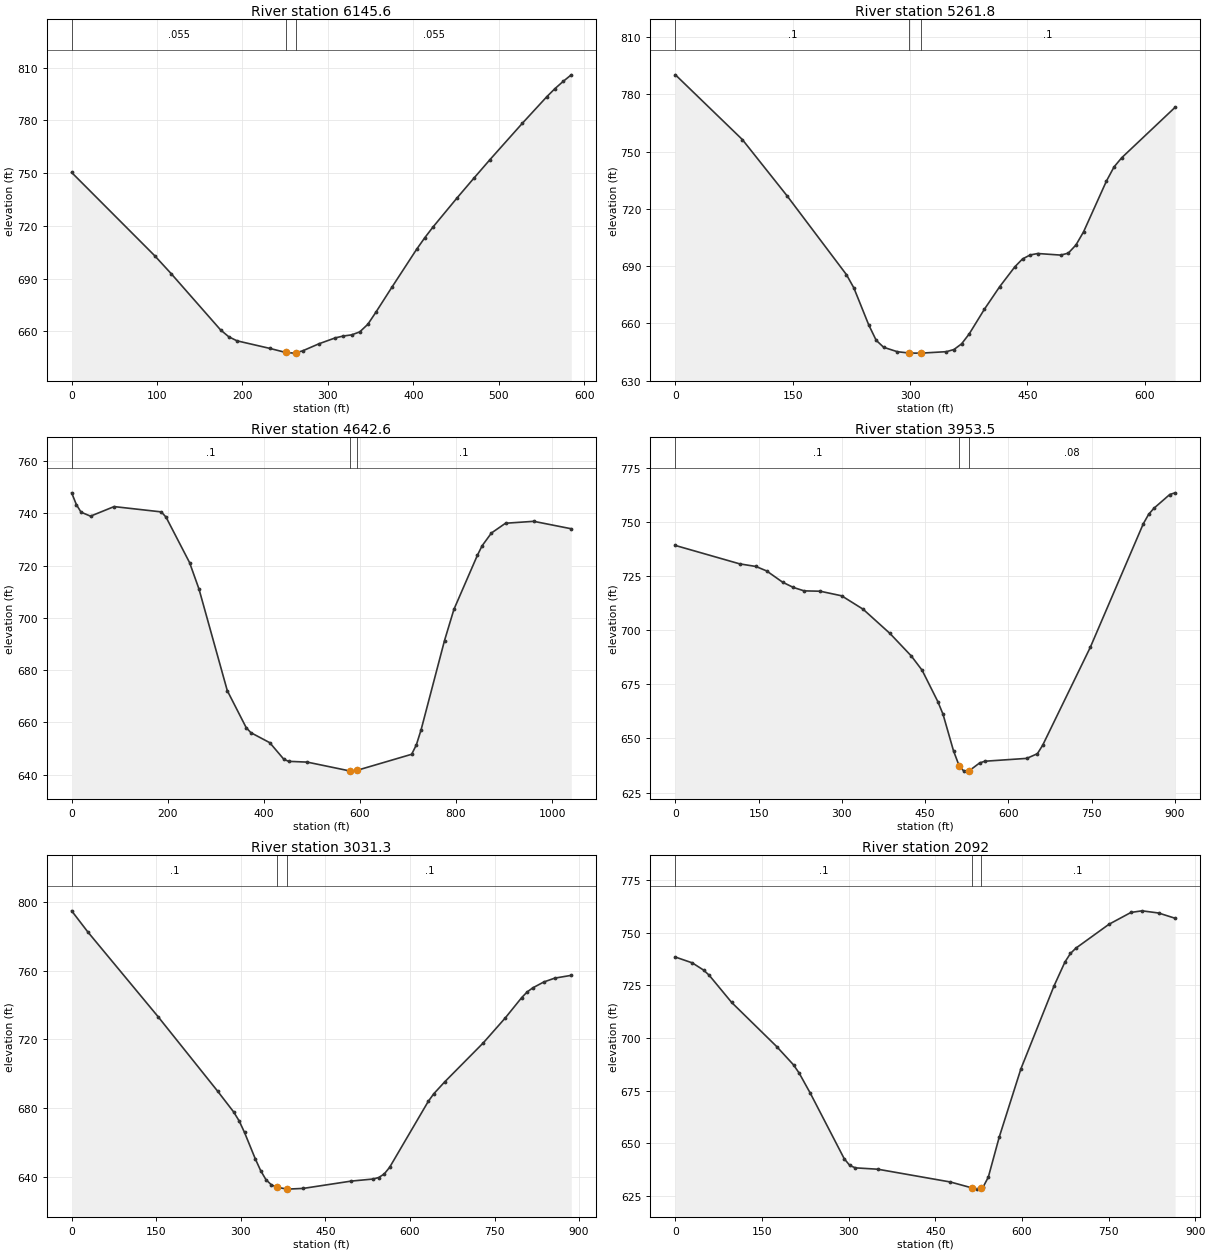
Type RM Length L Ch R = 1 ,6145.6  ,884.7,883.8,880.9
XS GIS Cut Line= 4
     1469028.633      221700.665     1469114.875      221829.693
     1469194.167      221949.778     1469368.584      222176.186
#Sta/Elev= 30
       0  750.35      97  703.15   116.4  692.91   174.4  660.84     184  656.94
   193.6  654.66   231.9  650.37   250.7  648.03   260.7  647.67  263.09647.9855
   270.3  648.94   289.5  652.98   308.6  656.33   318.2  657.41   327.7  658.04
   337.2  659.72   346.7  664.04   356.3  671.03   375.3  685.43   403.9  706.73
   413.4  713.26   422.9  719.28   451.5  736.08   470.6  746.95   489.6   757.6
   527.7  778.36   556.3  793.45   565.8  798.02   575.4  802.13   584.9  805.86
#Mann= 3 , 0 , 0
       0    .055       0   250.7    .045       0  263.09    .055       0
Bank Sta=250.7,263.09
XS Rating Curve= 0 ,0
Exp/Cntr=0.3,0.1

Type RM Length L Ch R = 1 ,5261.8  ,638.5,619.2,600.2
XS GIS Cut Line= 4
     1468324.313      222236.082     1468483.167      222449.624
     1468527.438      222504.311     1468748.792       222710.04
#Sta/Elev= 30
       0   790.2    85.6  756.27   142.6  726.87   218.6  685.53   228.1  678.57
   247.1   659.2   256.6  651.14   266.2  647.45   283.7  645.14   299.1  644.44
   301.3   644.4   314.1   644.4   346.3  645.16     356  646.28   365.8  649.26
   375.5  654.44     395  667.42   414.5  679.21     434  689.68   443.7  693.74
   453.5  695.83   463.2  696.59   492.5  695.76   502.2  696.78     512  701.06
   521.7  707.91     551  734.57   560.7  741.95   570.5  746.76   638.7  773.16
#Mann= 3 , 0 , 0
       0      .1       0   299.1    .045       0   314.1      .1       0
Bank Sta=299.1,314.1
XS Rating Curve= 0 ,0
Exp/Cntr=0.3,0.1

Type RM Length L Ch R = 1 ,4642.6  ,678.8,689.1,680.2
XS GIS Cut Line= 4
        1467504.      222975.665     1467971.602      222862.415
     1468139.417      222871.499     1468470.146      223079.832
#Sta/Elev= 30
       0  747.87     9.8  743.38    19.6  740.46    39.3  738.94    88.4   742.6
   186.6  740.57   196.4  738.59   245.5  721.16   265.1  711.03     324  672.14
   363.3     658   373.1  656.05   412.4  652.22   441.8  645.86   451.7  645.08
   490.5  644.78   578.8  641.41   583.8  641.33   593.8  641.62   707.8  647.78
   717.6  651.39   727.4  657.12   776.2  691.31   795.8  703.26   844.6  723.94
   854.4  727.58   873.9  732.49   903.2  736.23   961.9  736.96  1040.1  734.11
#Mann= 3 , 0 , 0
       0      .1       0   578.8    .045       0   593.8      .1       0
Bank Sta=578.8,593.8
XS Rating Curve= 0 ,0
Exp/Cntr=0.3,0.1

Type RM Length L Ch R = 1 ,3953.5  ,927.4,922.1,912.3
XS GIS Cut Line= 4
     1467688.896       223335.04       1468129.9      223391.245
     1468300.875      223337.644     1468563.896      223251.707
#Sta/Elev= 30
       0   739.1     116   730.6     145  729.41   164.3  727.36   193.3  722.13
   212.6  719.72     232  718.14   260.9  717.98   299.6  715.86   338.3  709.66
   386.6  698.49   425.2  688.05   444.6   681.5   472.9  667.03   482.3  661.17
   501.2  644.28   511.8  637.07     520  634.91   529.4  635.07   548.3  638.69
   557.7  639.48   633.3   640.8   652.4  642.96   661.9  646.88   747.8  692.12
   843.2   749.1   852.8  753.45   862.3  756.26   890.9  762.63   900.5  763.41
#Mann= 3 , 0 , 0
       0      .1       0   511.8    .045       0   529.4     .08       0
Bank Sta=511.8,529.4
XS Rating Curve= 0 ,0
Exp/Cntr=0.3,0.1

Type RM Length L Ch R = 1 ,3031.3  ,923.3,939.4,953.2
XS GIS Cut Line= 4
     1467905.042      224295.978     1468210.428      224182.664
      1468347.75      224082.436     1468681.084      223879.311
#Sta/Elev= 30
       0  795.01    28.7  782.69   153.3  733.27   258.7  689.92   287.4  677.68
     297  672.52   306.6  665.74   325.7  650.36   335.2  643.52   344.6  638.22
   354.1  635.24   364.4  633.78   382.4   632.7   410.7  633.12   495.7  637.38
   534.8   638.6   544.5  639.47   554.3  641.52     564  645.45   632.4  683.84
   642.1  688.27   661.6  695.25     730  717.99     769  732.53   798.3  744.46
     808  747.74   817.8  750.08   837.3   753.5   856.8  755.76   886.1  757.38
#Mann= 3 , 0 , 0
       0      .1       0   364.4    .045       0   382.4      .1       0
Bank Sta=364.4,382.4
XS Rating Curve= 0 ,0
Exp/Cntr=0.3,0.1

Type RM Length L Ch R = 1 ,2092    ,399.8,421.9,443.3
XS GIS Cut Line= 4
     1468319.105      224613.686     1468767.021      224624.103
     1468907.646      224621.499     1469183.688      224605.874
#Sta/Elev= 30
       0   738.4    29.2  735.65    48.7  732.24    58.4   729.8    97.4  716.87
   175.3  695.97   204.5  687.27   214.3  683.35   233.8   673.7   292.2   642.8
   301.9  639.55   311.7  638.41   350.6  637.76   476.2   631.7   513.9  628.87
     523  628.32   528.9  628.82   532.4  629.11   541.8  633.99   560.6  652.89
   598.2  685.34   655.4  724.58   674.5  736.05     684  740.11   693.6  742.66
   750.8  753.97   788.9  759.58     808  760.34   836.6  759.31   865.2  756.82
#Mann= 3 , 0 , 0
       0      .1       0   513.9    .045       0   528.9      .1       0
Bank Sta=513.9,528.9
XS Rating Curve= 0 ,0
Exp/Cntr=0.3,0.1

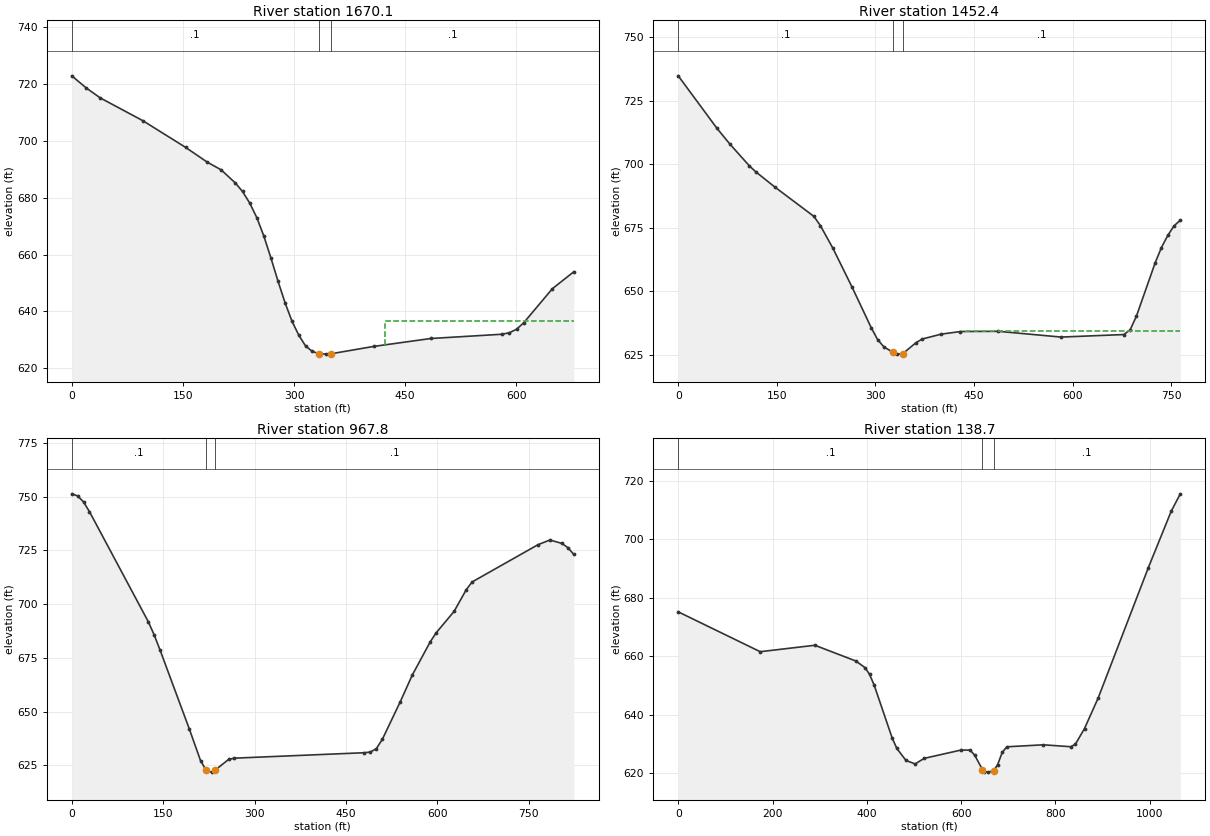
Type RM Length L Ch R = 1 ,1670.1  ,209,217.7,226.2
XS GIS Cut Line= 4
     1468311.292      224681.394     1468530.042      224868.894
     1468600.355      224965.249     1468714.938       225210.04
#Sta/Elev= 30
       0  722.78    19.2  718.59    38.4  715.03      96  707.01   153.7  697.64
   182.5  692.52   201.7  689.74   220.9  685.11   230.5  682.15   240.1  678.12
   249.7  673.01   259.3  666.47   268.9  658.73   278.5  650.54   288.1  642.91
   297.3  636.56   306.5  631.63   315.6  627.88   324.8  625.95  333.33625.2361
   343.2  625.02   349.6  625.13   407.4  627.72   484.6  630.51   581.1  632.01
   590.8  632.55   600.4  633.77   610.1  636.05   648.7     648   677.7  653.97
#Mann= 3 , 0 , 0
       0      .1       0  333.33    .045       0   349.6      .1       0
#XS Ineff= 2 , 0
                          422.58          636.66
Permanent Ineff=
       F       F
Bank Sta=333.33,349.6
XS Rating Curve= 0 ,0
Exp/Cntr=0.3,0.1

Type RM Length L Ch R = 1 ,1452.4  ,494.4,484.6,473
XS GIS Cut Line= 4
     1468178.722      224673.789     1468319.347      224824.831
     1468387.055      225077.435     1468540.701      225330.039
#Sta/Elev= 30
       0  734.79      59  714.08    78.6  707.89   108.1  699.35   117.9  696.98
   147.4  690.89   206.4  679.41   216.1  675.82   235.4  666.78   264.5  651.49
   293.5  635.58   303.2  630.89   312.9  627.99   326.3  625.92   332.3  625.16
   341.3   625.3   361.4  629.62     371  631.11   400.1  633.04   429.2  634.06
     487  634.14   582.3  631.88   677.7  632.87   687.2  634.69   696.8  640.08
   725.4  661.17   734.9  667.15   744.5   671.9     754  675.66   763.6  677.94
#Mann= 3 , 0 , 0
       0      .1       0   326.3    .045       0   341.3      .1       0
#XS Ineff= 2 , 0
                          438.12          634.29
Permanent Ineff=
       F       F
Bank Sta=326.3,341.3
XS Rating Curve= 0 ,0
Exp/Cntr=0.3,0.1

Type RM Length L Ch R = 1 ,967.8   ,859.7,829.1,798.2
XS GIS Cut Line= 4
     1467739.765      224900.489     1467889.417      225006.915
     1467974.047      225091.507        1468379.      225418.374
#Sta/Elev= 30
       0  751.37     9.7  750.39    19.3  747.59      29  743.09   125.6  691.79
   135.3   685.6     145   678.5   192.8  641.91   211.2  627.18   220.3  622.66
   229.7  621.77   235.3  622.73   257.3  627.68   266.5  628.27     480  630.81
   489.9  631.13   499.7   632.7   509.5  637.04     539   654.6   558.6  666.94
     588   682.4   597.9  686.68   627.3  696.65     647  706.64   656.8  710.33
   764.8  727.67   784.4  729.87   804.1  728.28   813.9  726.32   823.7  723.12
#Mann= 3 , 0 , 0
       0      .1       0   220.3    .045       0   235.3      .1       0
Bank Sta=220.3,235.3
XS Rating Curve= 0 ,0
Exp/Cntr=0.3,0.1

Type RM Length L Ch R = 1 ,138.7   ,152.1,138.7,121.8
XS GIS Cut Line= 4
     1467438.896      225769.936     1467957.125      225829.832
     1468144.625      225707.436     1468339.938      225454.832
#Sta/Elev= 30
       0  675.14   173.9  661.51   289.8  663.71   376.8  658.32   396.1  656.06
   405.8  653.75   415.4  650.14     454  631.87   463.7  628.39     483   624.3
   502.4  623.11   521.7  625.01   599.6  627.85     619  627.84   628.8   626.1
   645.3  621.15   648.2  620.44     658   620.3  668.98620.8114   677.4  622.86
   687.2  627.05   696.9  628.97   774.6  629.65   832.7  628.99   842.4  629.86
   861.7  635.22   890.7  645.67   997.2  690.31  1045.6  709.58  1064.9  715.53
#Mann= 3 , 0 , 0
       0      .1       0   645.3    .045       0  668.98      .1       0
Bank Sta=645.3,668.98
XS Rating Curve= 0 ,0
Exp/Cntr=0.3,0.1

Chan Stop Cuts=-1
Use User Specified Reach Order=0
Composite Channel Slope=5